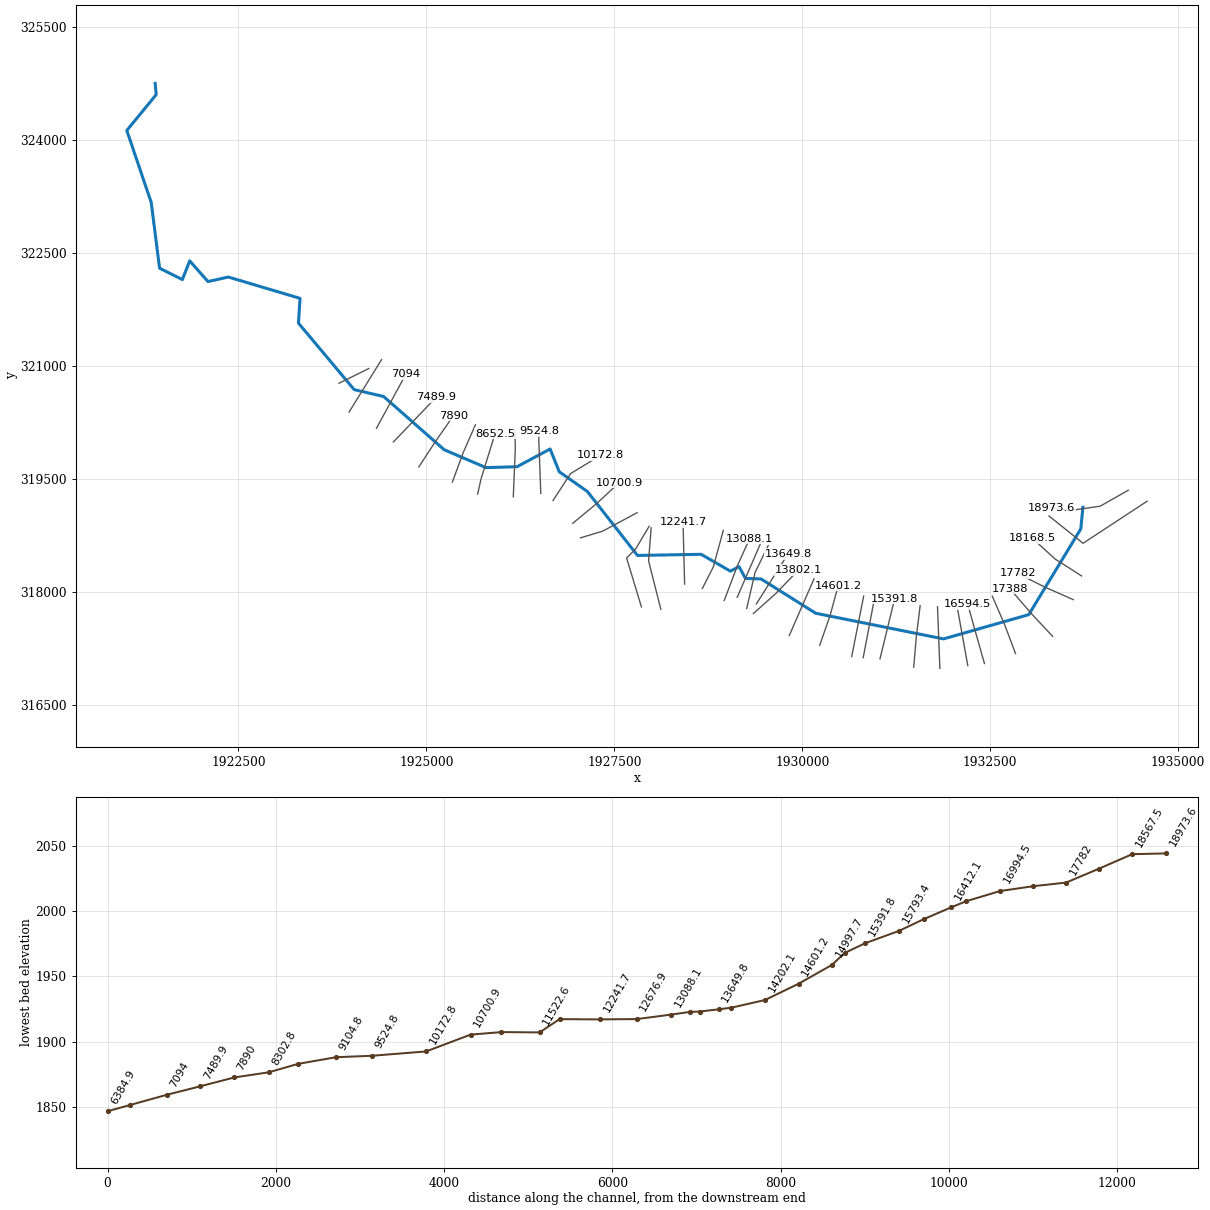
--- MllCrk.prj (project) ---

Proj Title=MllCrk
Current Plan=p01
Geom File=g01
Flow File=f01
Plan File=p01
DSS Export Rating Curves=0
DSS Export Rating Curve Sorted=0
DSS Export Volume Flow Curves=0
DXF OffsetX=0
DXF OffsetY=0
DXF ScaleX=0
DXF ScaleY=0

--- MllCrk.p01 (plan) ---

Plan Title=Floodplain
Program Version=4.00
Geom File=g01
Flow File=f01
K Sum by GR=0
Std Step Tol=0.01
Critical Tol=0.01
Num of Std Step Trials=20
Max Error Tol=0.3
Flow Tol Ratio=0.001
Split Flow NTrial=30
Split Flow Tol=0.02
Split Flow Ratio=0.02
Log Output Level=0
Friction Slope Method=1
Unsteady Friction Slope Method=2
Unsteady Bridges Friction Slope Method=1
Global Log Level=0
CheckData=False
Run HTab=0
Run UNet=0
Run PostProcess=0
UNET Theta=0
UNET Theta Warmup=0
UNET ZTol=0
UNET ZSATol=0
UNET MxIter=0
UNET MaxInSteps=0
UNET DtIC=0
UNET DtMin=0
UNET MaxCRTS=0
UNET WFStab=0
UNET SFStab=0
UNET WFX=0
UNET SFX=0
UNET DSS MLevel=0
UNET DZMax Abort=0
UNET Convert EG Bridges=0
UNET Use Existing IB Tables=0
UNET Froude Limit=0
UNET Froude Power=0
Write IC File=0
Echo Input=False
Echo Output=False
Write Detailed=0

--- MllCrk.f01 (steady flow) ---

Flow Title=NFF Regression Equation
Program Version=4.10
Number of Profiles= 1
Profile Names=P100yr
River Rch & RM=MllCrk,Main            ,18973.6
332.1351
River Rch & RM=MllCrk,Main            ,18567.5
537.6899
River Rch & RM=MllCrk,Main            ,17388
556.0473
River Rch & RM=MllCrk,Main            ,16994.5
620.1481
River Rch & RM=MllCrk,Main            ,13649.8
672.9647
River Rch & RM=MllCrk,Main            ,13425.5
760.6633
River Rch & RM=MllCrk,Main            ,11759.1
784.9832
River Rch & RM=MllCrk,Main            ,11067.7
1119.139
River Rch & RM=MllCrk,Main            ,10172.8
1132.761
River Rch & RM=MllCrk,Main            ,9524.8
1265.195
Boundary for River Rch & Prof#=MllCrk,Main            , 1
Up Type= 0
Dn Type= 1
Dn Known WS=1840.23
DSS Import GetInterval= 0
DSS Import GetPeak= 0
DSS Import FillOption= 0

--- MllCrk.g01 (geometry) ---

Geom Title=USGS 3m DEM
Program Version=4.00

River Reach=MllCrk     ,Main
Reach XY= 30
     1933732.843      319121.554     1933704.858      318835.244
     1933012.393      317697.392     1931877.792      317375.542
     1930178.598      317715.814     1929452.228      318170.949
     1929243.765      318178.215     1929159.129      318334.465
     1929043.244      318274.569     1928654.278      318497.960
     1927807.567      318482.903     1927142.202      319330.559
     1926767.202      319593.580     1926646.109      319895.663
     1926206.004      319659.986     1925793.244      319648.267
     1925237.067      319885.320     1924430.817      320591.872
     1924039.612      320682.900     1923298.452      321564.934
     1923319.328      321893.935     1922364.859      322176.913
     1922095.356      322116.257     1921851.855      322391.115
     1921754.182      322143.059     1921450.796      322294.101
     1921340.119      323165.195     1921015.058      324121.536
     1921406.107      324596.572     1921392.385      324746.740

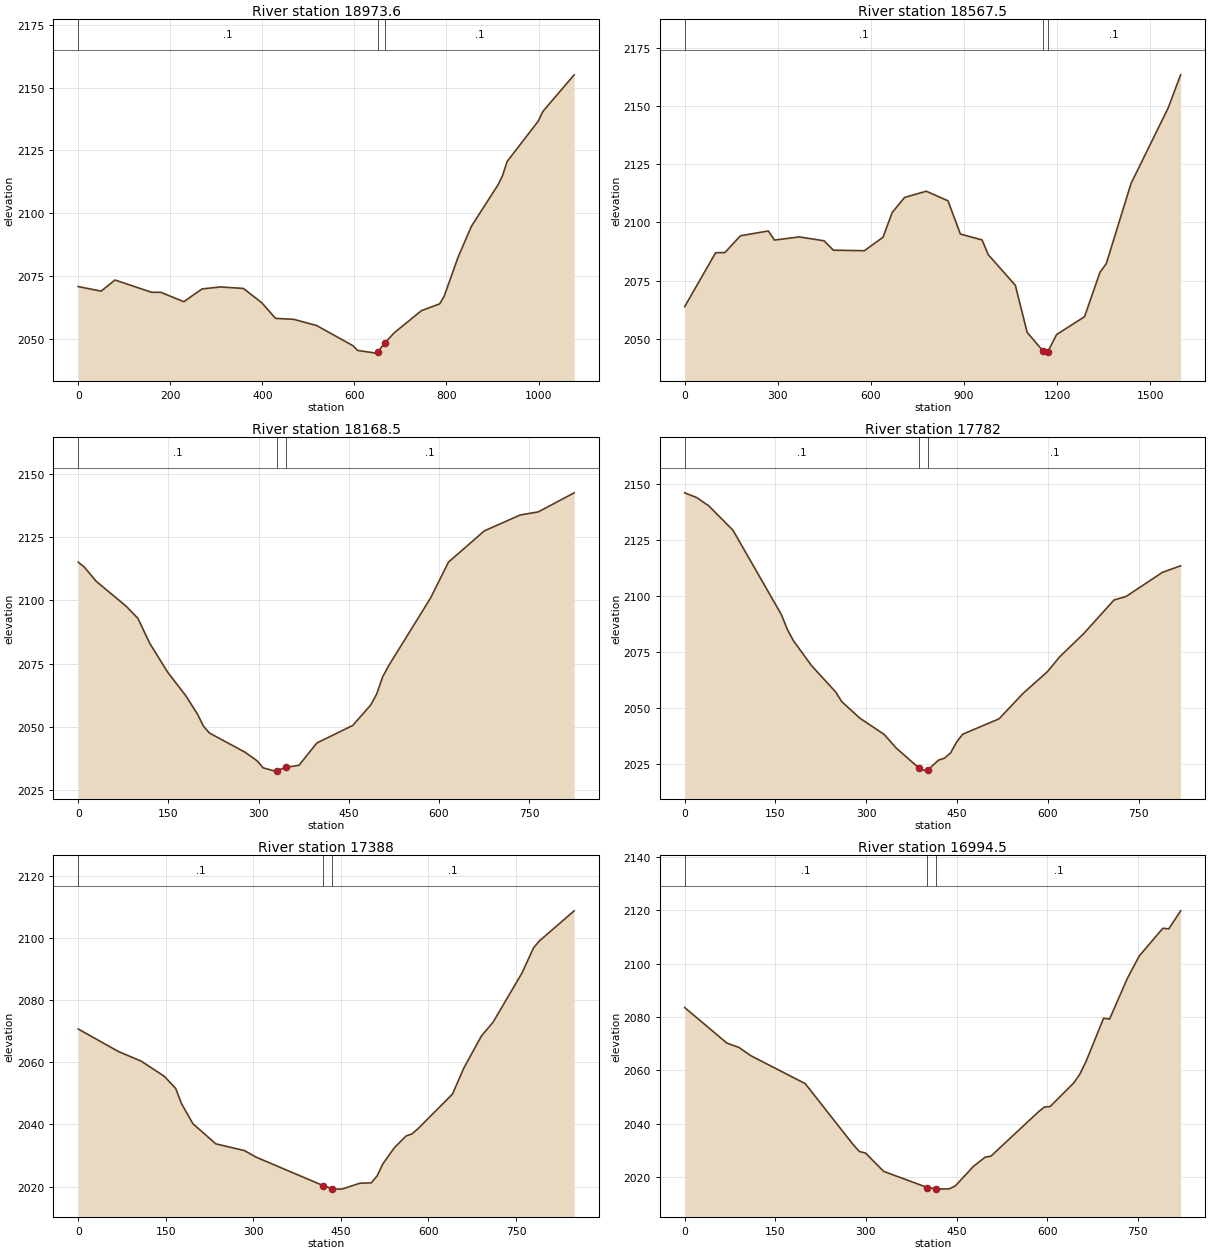
Type RM Length L Ch R = 1 ,18973.6,424.3,405.9,387.6
XS GIS Cut Line= 4
     1934335.553      319347.619     1933962.612      319136.330
     1933570.483      319079.953     1933320.346      319114.527
#Sta/Elev= 30
       0 2070.82    49.8 2068.99    79.8 2073.43   159.5 2068.54   179.4 2068.54
   229.3 2064.81   269.1 2069.88   309.0 2070.67   358.9 2070.07   398.7 2064.39
   428.6 2058.16   468.2 2057.77   517.8 2055.32   597.0 2047.27   606.9 2045.40
   646.5 2044.33     651 2044.87     666 2048.39   686.1 2052.36   745.6 2061.24
   785.2 2063.93   795.1 2067.04   824.8 2082.33   853.9 2094.73   912.2 2111.38
   921.9 2115.06   931.6 2120.56   999.6 2136.72  1009.3 2140.50  1077.3 2155.08
#Mann= 3 , 0 , 0
       0     0.1       0     651   0.045       0     666     0.1       0
Bank Sta=     651,     666
Exp/Cntr=0.3,0.1

Type RM Length L Ch R = 1 ,18567.5,396.7,399,401.3
XS GIS Cut Line= 4
     1934586.603      319202.227     1933734.833      318644.126
     1933601.928      318750.893     1933281.678      319006.120
#Sta/Elev= 30
       0 2063.76    99.8 2086.96   129.8 2087.06   179.7 2094.28   269.6 2096.33
   289.5 2092.42   369.4 2093.78   449.3 2092.10   479.2 2088.06   579.0 2087.84
   639.0 2093.61   668.9 2104.30   708.8 2110.79   778.7 2113.45   848.6 2109.33
   888.5 2095.02   958.4 2092.48   978.4 2086.12  1065.7 2072.94  1103.6 2052.72
  1155.4 2044.57  1160.4 2043.74  1170.4 2044.38  1198.8 2051.76  1288.7 2059.42
  1338.6 2078.62  1358.6 2082.22  1438.5 2116.78  1558.4 2149.38  1598.3 2163.57
#Mann= 3 , 0 , 0
       0     0.1       0  1155.4   0.045       0  1170.4     0.1       0
Bank Sta=  1155.4,  1170.4
Exp/Cntr=0.3,0.1

Type RM Length L Ch R = 1 ,18168.5,382.9,386.4,389.5
XS GIS Cut Line= 3
     1933715.599      318210.962     1933363.874      318434.805
     1933061.893      318709.447
#Sta/Elev= 30
       0 2115.08     9.9 2113.21    29.8 2107.56    79.4 2097.76    99.3 2092.88
   119.1 2082.99   148.9 2071.58   178.7 2062.40   198.5 2055.00   208.5 2050.22
   218.4 2047.55   277.9 2039.93   297.8 2036.54   307.7 2033.80   327.6 2032.50
   330.1 2032.65   345.1 2033.95   367.3 2034.82   397.1 2043.63   456.7 2050.54
   486.6 2058.63   496.6 2062.97   506.5 2069.76   516.5 2074.16   586.2 2100.92
   616.0 2115.10   675.8 2127.48   735.5 2133.74   765.4 2134.95   825.1 2142.49
#Mann= 3 , 0 , 0
       0     0.1       0   330.1   0.045       0   345.1     0.1       0
Bank Sta=   330.1,   345.1
Exp/Cntr=0.3,0.1

Type RM Length L Ch R = 1 ,17782,404,394.1,384.6
XS GIS Cut Line= 3
     1933604.846      317896.420     1933230.097      318061.260
     1932863.010      318244.012
#Sta/Elev= 30
       0 2146.25    20.0 2144.12    39.9 2140.43    79.9 2129.51   159.8 2091.86
   169.8 2085.17   179.7 2080.19   209.7 2069.07   249.6 2057.28   259.6 2052.98
   289.6 2045.58   329.5 2038.40   349.5 2032.27   387.1 2023.36   399.4 2021.96
   402.1 2022.56   419.4 2026.87   429.4 2027.76   439.4 2030.09   449.4 2034.96
   459.4 2038.45   519.4 2045.31   559.4 2056.74   599.4 2066.38   619.4 2072.93
   659.4 2083.39   709.4 2098.38   729.4 2099.97   789.5 2110.74   819.5 2113.66
#Mann= 3 , 0 , 0
       0     0.1       0   387.1   0.045       0   402.1     0.1       0
Bank Sta=   387.1,   402.1
Exp/Cntr=0.3,0.1

Type RM Length L Ch R = 1 ,17388,401.7,393.3,386
XS GIS Cut Line= 3
     1933329.341      317410.110     1933054.062      317704.021
     1932761.303      318041.751
#Sta/Elev= 30
       0 2070.69    68.8 2063.45   108.0 2060.33   147.3 2055.50   167.0 2051.57
   176.8 2046.74   196.4 2040.23   235.7 2033.74   284.8 2031.57   304.5 2029.48
     420 2020.27     435 2019.32   442.4 2019.17   452.4 2019.20   482.2 2021.06
   502.0 2021.19   512.0 2023.41   521.9 2027.29   541.8 2032.53   561.6 2036.27
   571.5 2036.90   581.5 2038.50   641.1 2049.73   660.9 2058.23   690.7 2068.43
   710.6 2072.84   760.3 2088.73   780.1 2096.81   790.1 2099.02   849.6 2108.70
#Mann= 3 , 0 , 0
       0     0.1       0     420   0.045       0     435     0.1       0
Bank Sta=     420,     435
Exp/Cntr=0.3,0.1

Type RM Length L Ch R = 1 ,16994.5,401.9,400.1,397
XS GIS Cut Line= 3
     1932836.196      317181.033     1932692.130      317563.805
     1932528.328      317941.524
#Sta/Elev= 30
       0 2083.56    69.8 2070.23    89.8 2068.58   109.7 2065.45   199.5 2055.01
   279.3 2032.00   289.3 2029.53   299.3 2028.96   329.2 2022.10   401.5 2016.04
   416.5 2015.54   418.8 2015.43   438.4 2015.57   448.2 2016.69   477.6 2023.93
   497.2 2027.40   507.0 2027.84   585.4 2044.43   595.2 2046.23   605.0 2046.45
   644.2 2055.34   654.0 2058.60   663.8 2063.10   693.3 2079.57   703.1 2079.22
   732.5 2094.47   752.1 2102.86   791.3 2113.30   801.1 2113.07   820.7 2119.84
#Mann= 3 , 0 , 0
       0     0.1       0   401.5   0.045       0   416.5     0.1       0
Bank Sta=   401.5,   416.5
Exp/Cntr=0.3,0.1

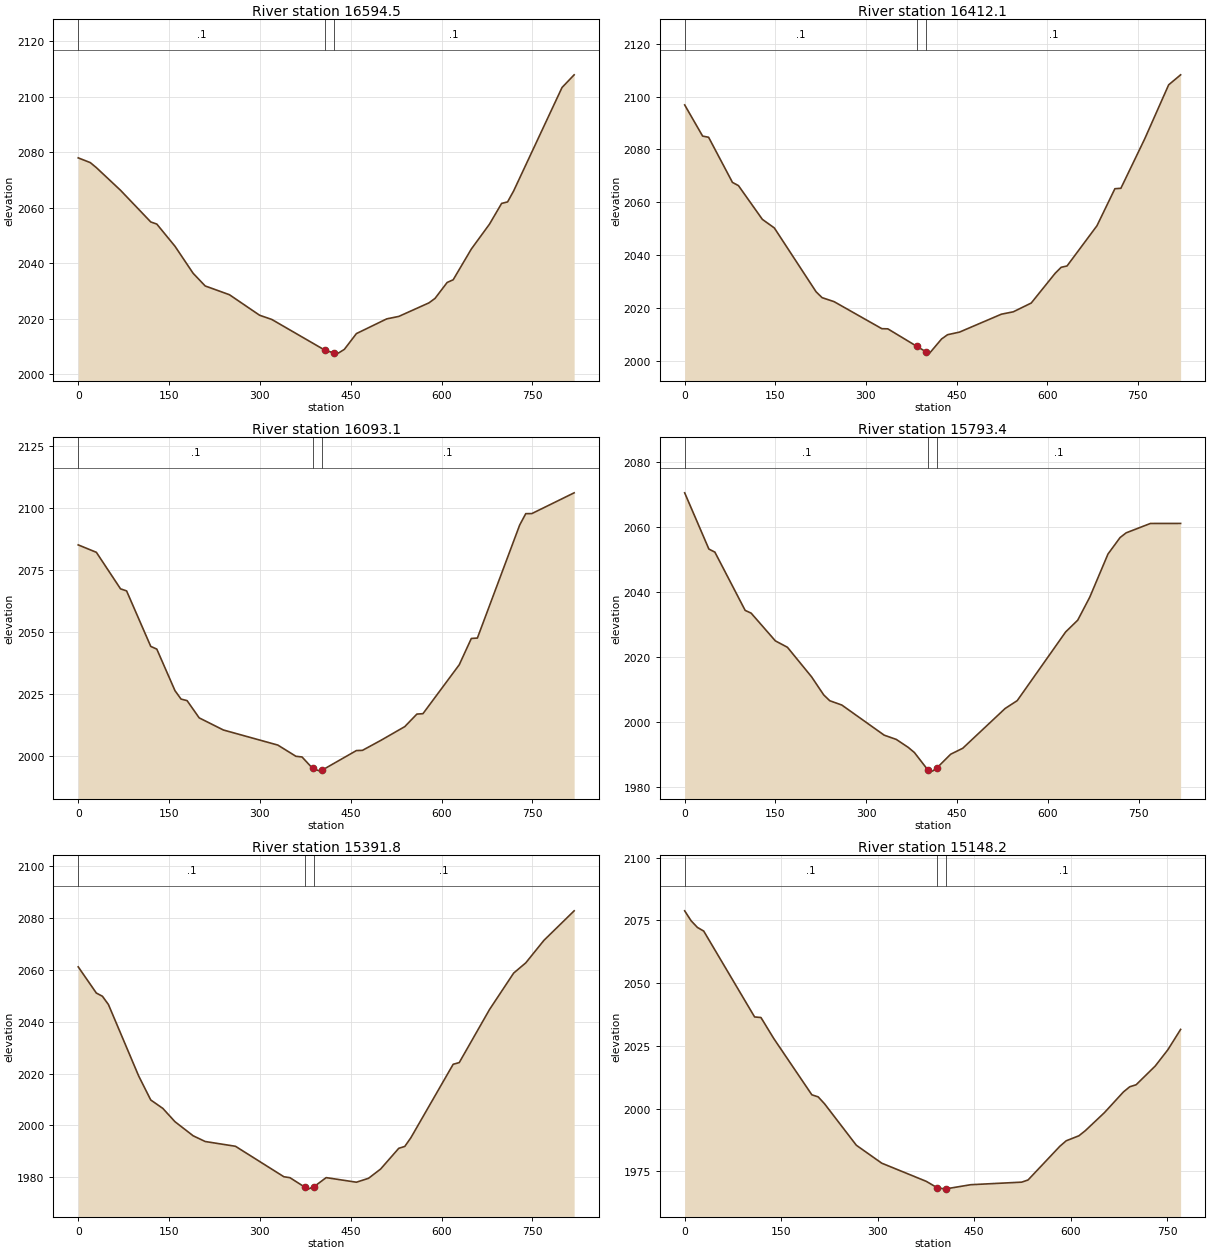
Type RM Length L Ch R = 1 ,16594.5,184.5,182.3,180.2
XS GIS Cut Line= 3
     1932423.051      317049.308     1932310.819      317443.127
     1932200.240      317837.419
#Sta/Elev= 30
       0 2078.01    20.0 2076.30    30.0 2074.49    69.9 2066.33   119.8 2054.93
   129.8 2054.16   159.8 2046.18   189.8 2036.43   209.7 2031.87   249.7 2028.72
   299.6 2021.32   319.6 2019.82     407 2008.79     422 2007.74   429.5 2007.68
   439.5 2009.03   459.4 2014.71   509.4 2020.01   529.4 2020.90   579.3 2025.79
   589.3 2027.40   609.3 2033.14   619.2 2034.09   649.2 2045.17   679.2 2054.14
   699.2 2061.60   709.1 2062.15   719.1 2066.11   799.0 2103.36   819.0 2107.92
#Mann= 3 , 0 , 0
       0     0.1       0     407   0.045       0     422     0.1       0
Bank Sta=     407,     422
Exp/Cntr=0.3,0.1

Type RM Length L Ch R = 1 ,16412.1,322.1,318.9,315.7
XS GIS Cut Line= 2
     1932201.418      317021.961     1932055.170      317829.808
#Sta/Elev= 30
       0 2096.84    29.7 2085.04    39.6 2084.60    79.1 2067.51    89.0 2066.30
   128.6 2053.52   148.4 2050.28   217.6 2026.09   227.5 2023.89   247.3 2022.38
   326.4 2012.14   336.3 2012.08   384.6 2005.42   399.6 2003.38   405.5 2002.89
   425.3 2008.25   435.2 2009.86   455.0 2010.85   524.2 2017.62   544.0 2018.53
   573.7 2021.85   613.3 2033.10   623.2 2035.37   633.0 2035.89   682.5 2051.10
   712.2 2065.12   722.1 2065.28   761.6 2084.01   801.2 2104.44   821.0 2108.23
#Mann= 3 , 0 , 0
       0     0.1       0   384.6   0.045       0   399.6     0.1       0
Bank Sta=   384.6,   399.6
Exp/Cntr=0.3,0.1

Type RM Length L Ch R = 1 ,16093.1,302.6,299.7,296.1
XS GIS Cut Line= 3
     1931830.281      316984.524     1931814.543      317393.722
     1931798.805      317802.919
#Sta/Elev= 30
       0 2085.19    30.0 2082.19    69.9 2067.47    79.9 2066.64   119.8 2044.28
   129.8 2043.18   159.8 2026.45   169.8 2023.05   179.8 2022.42   199.8 2015.47
   239.7 2010.59   329.6 2004.51   359.6 1999.98   369.6 1999.72   387.1 1995.11
   399.5 1994.01   402.1 1994.31   459.4 2002.30   469.4 2002.38   499.4 2006.35
   539.3 2011.95   559.3 2017.00   569.3 2017.16   629.2 2036.86   649.2 2047.47
   659.2 2047.64   729.1 2093.22   739.1 2097.78   749.1 2097.80   819.0 2106.17
#Mann= 3 , 0 , 0
       0     0.1       0   387.1   0.045       0   402.1     0.1       0
Bank Sta=   387.1,   402.1
Exp/Cntr=0.3,0.1

Type RM Length L Ch R = 1 ,15793.4,405.2,401.7,399.1
XS GIS Cut Line= 3
     1931482.141      317000.835     1931517.556      317408.742
     1931567.863      317815.474
#Sta/Elev= 30
       0 2070.40    40.0 2053.12    49.9 2052.18    99.9 2034.28   109.8 2033.43
   149.8 2024.91   169.8 2022.93   209.7 2013.84   229.7 2008.30   239.7 2006.51
   259.6 2005.19   329.6 1995.93   349.5 1994.63   369.5 1992.15   379.5 1990.60
   401.9 1985.21   409.4 1984.88   416.9 1985.90   439.4 1990.07   459.4 1991.91
   529.4 2004.13   549.4 2006.55   629.4 2027.66   649.3 2031.26   669.3 2038.37
   699.3 2051.59   719.3 2056.66   729.3 2058.10   769.3 2060.98   819.3 2061.00
#Mann= 3 , 0 , 0
       0     0.1       0   401.9   0.045       0   416.9     0.1       0
Bank Sta=   401.9,   416.9
Exp/Cntr=0.3,0.1

Type RM Length L Ch R = 1 ,15391.8,242.2,243.4,244.6
XS GIS Cut Line= 3
     1931033.604      317110.751     1931130.841      317508.539
     1931228.078      317906.327
#Sta/Elev= 30
       0 2061.17    30.0 2051.05    40.0 2049.82    49.9 2046.64    99.9 2019.05
   119.8 2009.81   139.8 2006.55   159.8 2001.43   189.8 1996.00   209.7 1993.79
   259.7 1991.95   339.6 1980.20   349.6 1979.84   374.5 1976.14   379.5 1975.42
   389.5 1976.37   409.5 1979.86   459.4 1978.09   479.4 1979.59   499.4 1983.17
   529.4 1991.17   539.3 1991.89   549.3 1995.22   619.2 2023.58   629.2 2024.23
   679.2 2044.69   719.1 2058.76   739.1 2062.71   769.1 2071.39   819.0 2082.78
#Mann= 3 , 0 , 0
       0     0.1       0   374.5   0.045       0   389.5     0.1       0
Bank Sta=   374.5,   389.5
Exp/Cntr=0.3,0.1

Type RM Length L Ch R = 1 ,15148.2,150.7,150.6,150.4
XS GIS Cut Line= 2
     1930810.319      317126.424     1930954.826      317883.781
#Sta/Elev= 30
       0 2078.80     9.9 2074.87    19.8 2072.19    29.6 2070.74   108.7 2036.54
   118.6 2036.30   138.4 2027.98   197.7 2005.53   207.6 2004.69   217.5 2001.93
   266.9 1985.43   306.4 1978.29   375.6 1971.06     392 1968.60   405.3 1967.96
     407 1968.11   444.8 1969.72   523.9 1970.74   533.8 1971.60   583.2 1985.01
   593.1 1987.21   612.9 1989.21   622.8 1991.23   652.4 1998.38   682.1 2006.67
   691.9 2008.72   701.8 2009.52   731.5 2016.98   751.2 2023.48   771.0 2031.57
#Mann= 3 , 0 , 0
       0     0.1       0     392   0.045       0     407     0.1       0
Bank Sta=     392,     407
Exp/Cntr=0.3,0.1

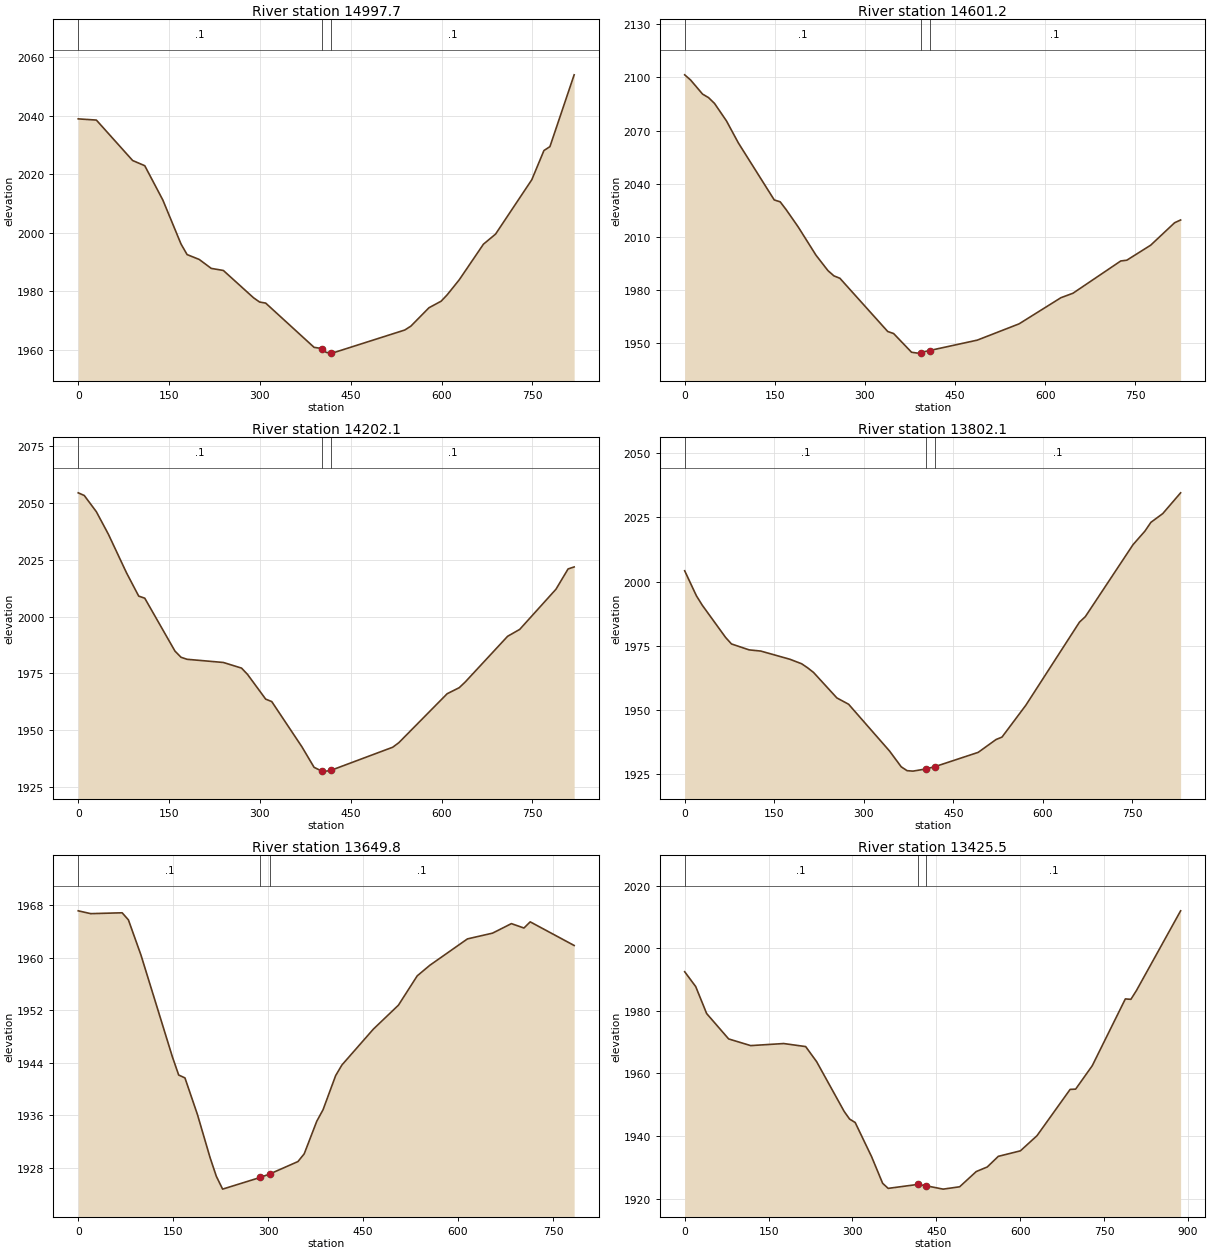
Type RM Length L Ch R = 1 ,14997.7,399.7,396.6,393.8
XS GIS Cut Line= 3
     1930657.427      317140.979     1930737.040      317542.665
     1930816.654      317944.352
#Sta/Elev= 30
       0 2038.86    30.0 2038.45    89.9 2024.63   109.9 2022.86   139.8 2011.12
   169.8 1996.10   179.8 1992.50   199.8 1990.84   219.7 1987.78   239.7 1987.07
   289.6 1977.73   299.6 1976.28   309.6 1975.92   389.5 1960.81     402 1960.41
   409.5 1959.09     417 1958.90   419.5 1958.83   539.3 1966.73   549.3 1968.04
   579.3 1974.34   599.3 1976.57   609.3 1978.75   629.2 1983.87   669.2 1996.05
   689.2 1999.49   749.1 2018.09   769.1 2028.04   779.0 2029.38   819.0 2053.91
#Mann= 3 , 0 , 0
       0     0.1       0     402   0.045       0     417     0.1       0
Bank Sta=     402,     417
Exp/Cntr=0.3,0.1

Type RM Length L Ch R = 1 ,14601.2,400.5,398.9,396.8
XS GIS Cut Line= 3
     1930231.931      317291.606     1930369.774      317685.560
     1930477.462      318079.206
#Sta/Elev= 30
       0 2101.44     9.9 2098.50    29.8 2090.56    39.8 2088.56    49.7 2085.29
    69.6 2075.41    89.4 2062.98   149.1 2030.84   159.0 2029.77   168.9 2025.36
   188.8 2015.69   218.6 1999.64   238.5 1990.95   248.4 1988.00   258.4 1986.62
   337.9 1956.62   347.8 1955.44   377.6 1944.89   387.6 1944.39   392.7 1944.73
   407.7 1945.86   487.0 1951.72   556.7 1960.92   626.4 1975.69   646.3 1978.18
   725.9 1996.40   735.9 1996.82   775.7 2005.31   815.5 2017.97   825.5 2019.52
#Mann= 3 , 0 , 0
       0     0.1       0   392.7   0.045       0   407.7     0.1       0
Bank Sta=   392.7,   407.7
Exp/Cntr=0.3,0.1

Type RM Length L Ch R = 1 ,14202.1,409.6,399.8,391.9
XS GIS Cut Line= 3
     1929827.566      317421.628     1929991.702      317796.794
     1930155.837      318171.960
#Sta/Elev= 30
       0 2054.52    10.0 2053.35    30.0 2046.18    49.9 2036.24    79.9 2019.20
    99.9 2009.02   109.9 2008.10   159.8 1984.79   169.8 1982.07   179.8 1981.18
   239.7 1979.78   269.7 1977.30   279.7 1974.50   309.6 1963.63   319.6 1962.55
   369.6 1942.55   389.5 1933.59     402 1931.94   409.5 1931.91     417 1932.22
   519.4 1942.44   529.4 1944.42   609.3 1966.01   629.2 1968.67   639.2 1971.20
   709.1 1991.31   729.1 1994.35   789.0 2012.06   809.0 2020.99   819.0 2021.87
#Mann= 3 , 0 , 0
       0     0.1       0     402   0.045       0     417     0.1       0
Bank Sta=     402,     417
Exp/Cntr=0.3,0.1

Type RM Length L Ch R = 1 ,13802.1,145.7,152.2,156.8
XS GIS Cut Line= 3
     1929350.259      317712.304     1929657.665      317986.432
     1929947.384      318289.068
#Sta/Elev= 30
       0 2004.19    19.6 1994.45    29.4 1990.78    68.6 1978.16    78.4 1975.64
   107.9 1973.33   127.5 1972.86   176.5 1969.65   196.1 1967.89   205.9 1966.34
   215.8 1964.54   255.0 1954.57   274.6 1952.12   343.2 1933.86   362.8 1927.69
   372.6 1926.20   382.5 1926.02   404.4 1926.89   419.4 1927.78   491.7 1933.34
   521.6 1938.35   531.6 1939.30   571.5 1951.72   661.3 1984.13   671.2 1986.30
   751.0 2014.35   771.0 2019.66   781.0 2023.08   800.9 2026.50   830.8 2034.60
#Mann= 3 , 0 , 0
       0     0.1       0   404.4   0.045       0   419.4     0.1       0
Bank Sta=   404.4,   419.4
Exp/Cntr=0.3,0.1

Type RM Length L Ch R = 1 ,13649.8,216.8,224.5,232
XS GIS Cut Line= 2
     1929389.622      317840.254     1929809.215      318501.853
#Sta/Elev= 30
       0 1967.18    19.8 1966.75    69.4 1966.88    79.3 1965.80    99.2 1960.42
   148.8 1944.92   158.7 1942.16   168.6 1941.72   188.4 1936.12   208.3 1929.57
   218.2 1926.72   228.1 1924.77   287.8 1926.56   302.8 1927.09   347.1 1928.97
   357.0 1930.15   376.8 1935.11   386.8 1936.88   406.6 1942.06   416.5 1943.68
   466.1 1949.14   505.8 1952.80   535.5 1957.27   555.4 1958.88   614.8 1962.90
   654.5 1963.78   684.3 1965.23   704.1 1964.56   714.0 1965.50   783.4 1961.90
#Mann= 3 , 0 , 0
       0     0.1       0   287.8   0.045       0   302.8     0.1       0
Bank Sta=   287.8,   302.8
Exp/Cntr=0.3,0.1

Type RM Length L Ch R = 1 ,13425.5,123.1,118,112.7
XS GIS Cut Line= 3
     1929260.542      317778.822     1929372.214      318257.519
     1929545.710      318612.400
#Sta/Elev= 30
       0 1992.49    19.7 1987.76    39.3 1979.13    78.6 1971.03   118.0 1968.90
   177.0 1969.56   216.3 1968.59   235.9 1963.77   285.1 1947.89   294.9 1945.43
   304.8 1944.35   334.2 1933.41   353.9 1924.93   363.8 1923.31   416.6 1924.57
   431.6 1924.14   462.1 1923.07   491.6 1923.82   521.2 1928.68   540.9 1930.14
   560.7 1933.54   600.2 1935.30   629.8 1940.12   689.1 1954.92   698.9 1955.00
   728.6 1962.47   787.8 1983.81   797.7 1983.68   807.6 1986.48   886.6 2011.94
#Mann= 3 , 0 , 0
       0     0.1       0   416.6   0.045       0   431.6     0.1       0
Bank Sta=   416.6,   431.6
Exp/Cntr=0.3,0.1

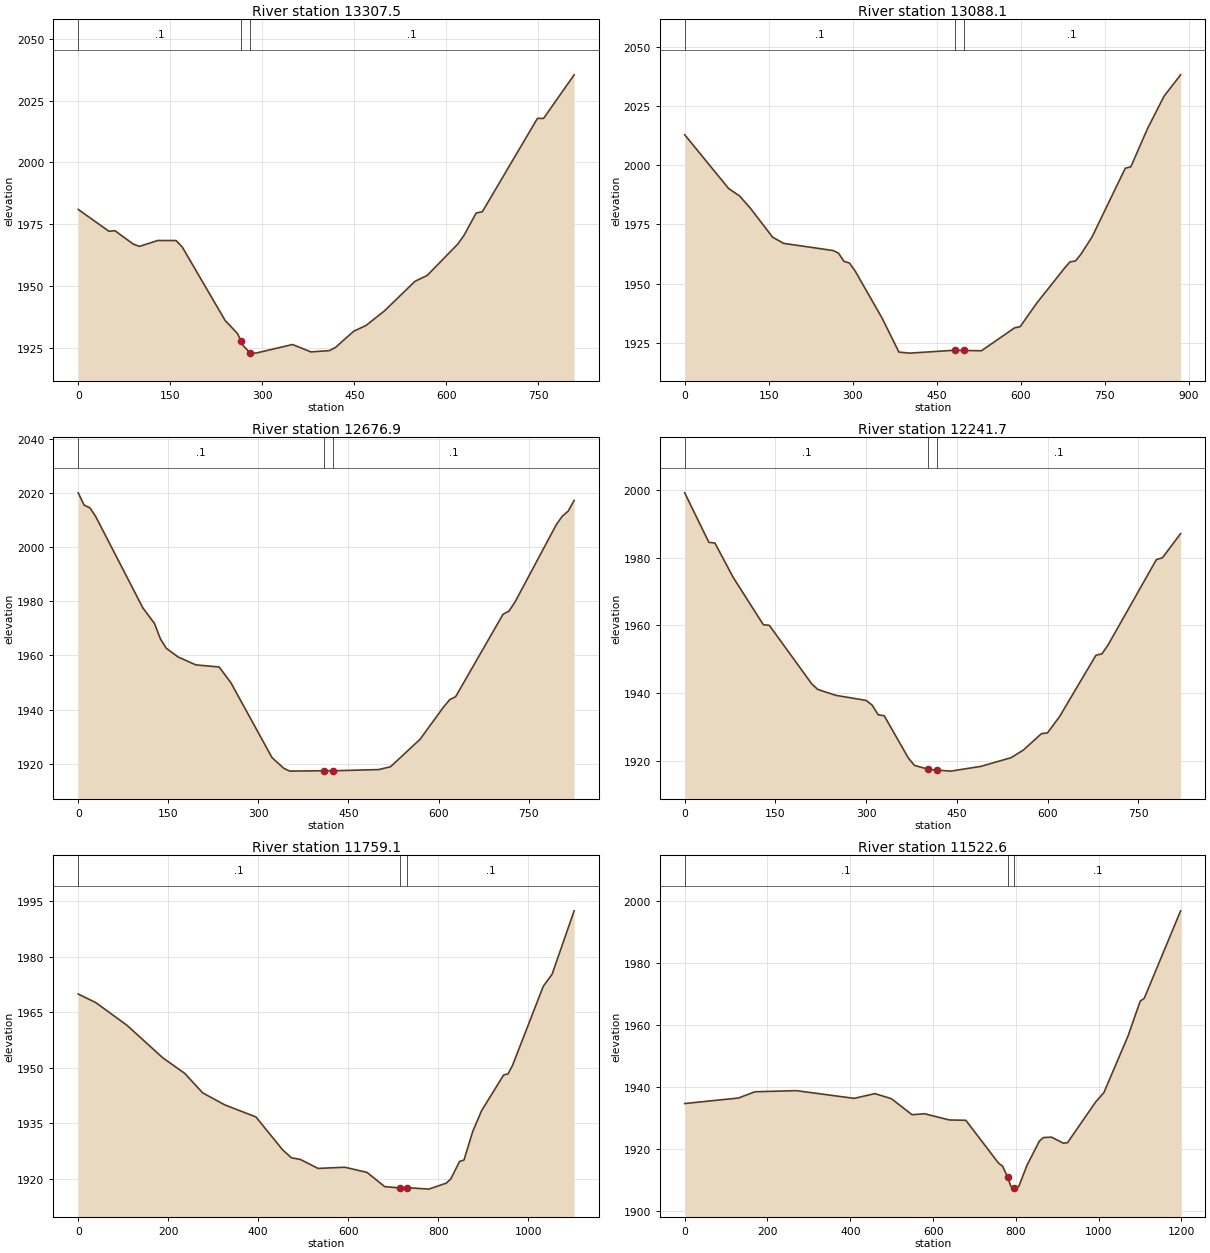
Type RM Length L Ch R = 1 ,13307.5,219.2,219.4,217.8
XS GIS Cut Line= 2
     1929134.567      317928.418     1929456.778      318669.648
#Sta/Elev= 30
       0 1980.95    49.9 1972.13    59.9 1972.32    89.8 1966.90    99.8 1965.98
   129.7 1968.37   159.6 1968.34   169.6 1965.71   239.5 1935.97   259.4 1930.78
   265.5 1927.64   269.4 1925.64   280.5 1922.82   289.4 1922.78   349.2 1926.26
   379.2 1923.28   409.1 1923.78   419.1 1925.06   449.0 1931.65   469.0 1933.96
   498.9 1939.84   548.8 1951.84   568.8 1954.24   618.6 1966.92   628.6 1970.42
   648.6 1979.49   658.6 1980.00   748.4 2017.80   758.3 2017.77   808.2 2035.42
#Mann= 3 , 0 , 0
       0     0.1       0   265.5   0.045       0   280.5     0.1       0
Bank Sta=   265.5,   280.5
Exp/Cntr=0.3,0.1

Type RM Length L Ch R = 1 ,13088.1,405.7,411.1,416.9
XS GIS Cut Line= 3
     1928962.342      317886.232     1929136.039      318344.961
     1929299.577      318704.741
#Sta/Elev= 30
       0 2012.87    78.5 1990.16    98.1 1987.02   117.7 1981.75   157.0 1969.66
   176.6 1967.04   264.9 1964.02   274.7 1962.91   284.5 1959.45   294.3 1958.73
   304.1 1955.52   353.2 1935.23   382.6 1921.17   402.2 1920.74     483 1921.97
     498 1921.86   530.0 1921.73   589.3 1931.42   599.2 1931.91   628.8 1941.85
   678.2 1956.54   688.1 1959.22   698.0 1959.60   707.9 1962.54   727.6 1969.78
   786.9 1998.74   796.8 1999.32   826.4 2015.32   856.1 2029.12   885.7 2038.12
#Mann= 3 , 0 , 0
       0     0.1       0     483   0.045       0     498     0.1       0
Bank Sta=     483,     498
Exp/Cntr=0.3,0.1

Type RM Length L Ch R = 1 ,12676.9,428.6,435.2,441.9
XS GIS Cut Line= 3
     1928670.566      318043.599     1928816.817      318331.231
     1928949.967      318816.280
#Sta/Elev= 30
       0 2019.98     9.8 2015.46    19.6 2014.42    29.3 2011.16   107.6 1977.54
   127.1 1971.72   136.9 1966.05   146.7 1962.60   166.2 1959.42   195.6 1956.50
   234.7 1955.70   254.2 1949.91   322.7 1922.26   342.4 1918.30   352.3 1917.28
   409.6 1917.42   424.6 1917.41   500.2 1917.85   519.9 1918.89   569.2 1929.04
   608.7 1941.07   618.6 1943.67   628.4 1944.76   707.3 1975.16   717.2 1976.35
   727.0 1979.60   796.1 2008.28   806.0 2011.36   815.8 2013.23   825.7 2017.19
#Mann= 3 , 0 , 0
       0     0.1       0   409.6   0.045       0   424.6     0.1       0
Bank Sta=   409.6,   424.6
Exp/Cntr=0.3,0.1

Type RM Length L Ch R = 1 ,12241.7,485.2,482.5,479.6
XS GIS Cut Line= 2
     1928434.928      318102.932     1928413.586      318922.514
#Sta/Elev= 30
       0 1999.11    40.0 1984.51    50.0 1984.31    80.0 1974.24   130.0 1960.23
   140.0 1960.03   210.0 1942.79   220.0 1941.13   250.0 1939.39   300.0 1937.90
   310.0 1936.50   320.0 1933.66   329.9 1933.38   369.9 1920.88   379.9 1918.74
   402.4 1917.62   417.4 1917.34   439.9 1917.05   489.9 1918.46   539.9 1921.03
   559.9 1923.26   589.9 1928.11   599.9 1928.33   619.9 1933.17   679.9 1951.22
   689.9 1951.64   699.9 1954.24   779.9 1979.43   789.9 1979.97   819.9 1987.09
#Mann= 3 , 0 , 0
       0     0.1       0   402.4   0.045       0   417.4     0.1       0
Bank Sta=   402.4,   417.4
Exp/Cntr=0.3,0.1

Type RM Length L Ch R = 1 ,11759.1,252.8,236.4,220.1
XS GIS Cut Line= 3
     1928118.685      317768.246     1927955.894      318409.537
     1927989.608      318849.025
#Sta/Elev= 30
       0 1969.89    39.5 1967.54   108.6 1961.43   187.6 1952.71   237.0 1948.45
   276.5 1943.23   325.9 1939.96   395.0 1936.72   454.2 1927.86   474.0 1925.68
   493.8 1925.24   533.2 1922.82   592.5 1923.14   641.9 1921.75   681.2 1917.91
   715.3 1917.54   730.3 1917.64   779.2 1917.23   818.4 1918.86   828.2 1919.99
   847.7 1924.70   857.5 1925.08   877.1 1932.84   896.7 1938.41   945.7 1948.04
   955.5 1948.34   965.3 1950.58  1033.8 1971.98  1053.4 1975.23  1102.4 1992.34
#Mann= 3 , 0 , 0
       0     0.1       0   715.3   0.045       0   730.3     0.1       0
Bank Sta=   715.3,   730.3
Exp/Cntr=0.3,0.1

Type RM Length L Ch R = 1 ,11522.6,461.9,454.9,448
XS GIS Cut Line= 4
     1927860.531      317799.793     1927662.990      318449.578
     1927782.507      318567.031     1927962.550      318868.640
#Sta/Elev= 30
       0 1934.63   129.8 1936.40   169.8 1938.41   269.7 1938.78   409.5 1936.29
   459.4 1937.82   499.4 1936.19   549.3 1931.02   579.3 1931.34   639.2 1929.34
   679.2 1929.23   758.0 1915.47   767.9 1914.44   780.3 1910.89   787.6 1908.06
   795.3 1907.27   797.4 1907.06   807.3 1908.00   827.0 1914.76   856.5 1922.46
   866.2 1923.66   885.8 1923.81   915.0 1921.85   924.8 1922.02   993.1 1935.19
  1012.6 1938.13  1071.1 1956.42  1100.4 1967.61  1110.2 1968.52  1198.0 1996.69
#Mann= 3 , 0 , 0
       0     0.1       0   780.3   0.045       0   795.3     0.1       0
Bank Sta=   780.3,   795.3
Exp/Cntr=0.3,0.1

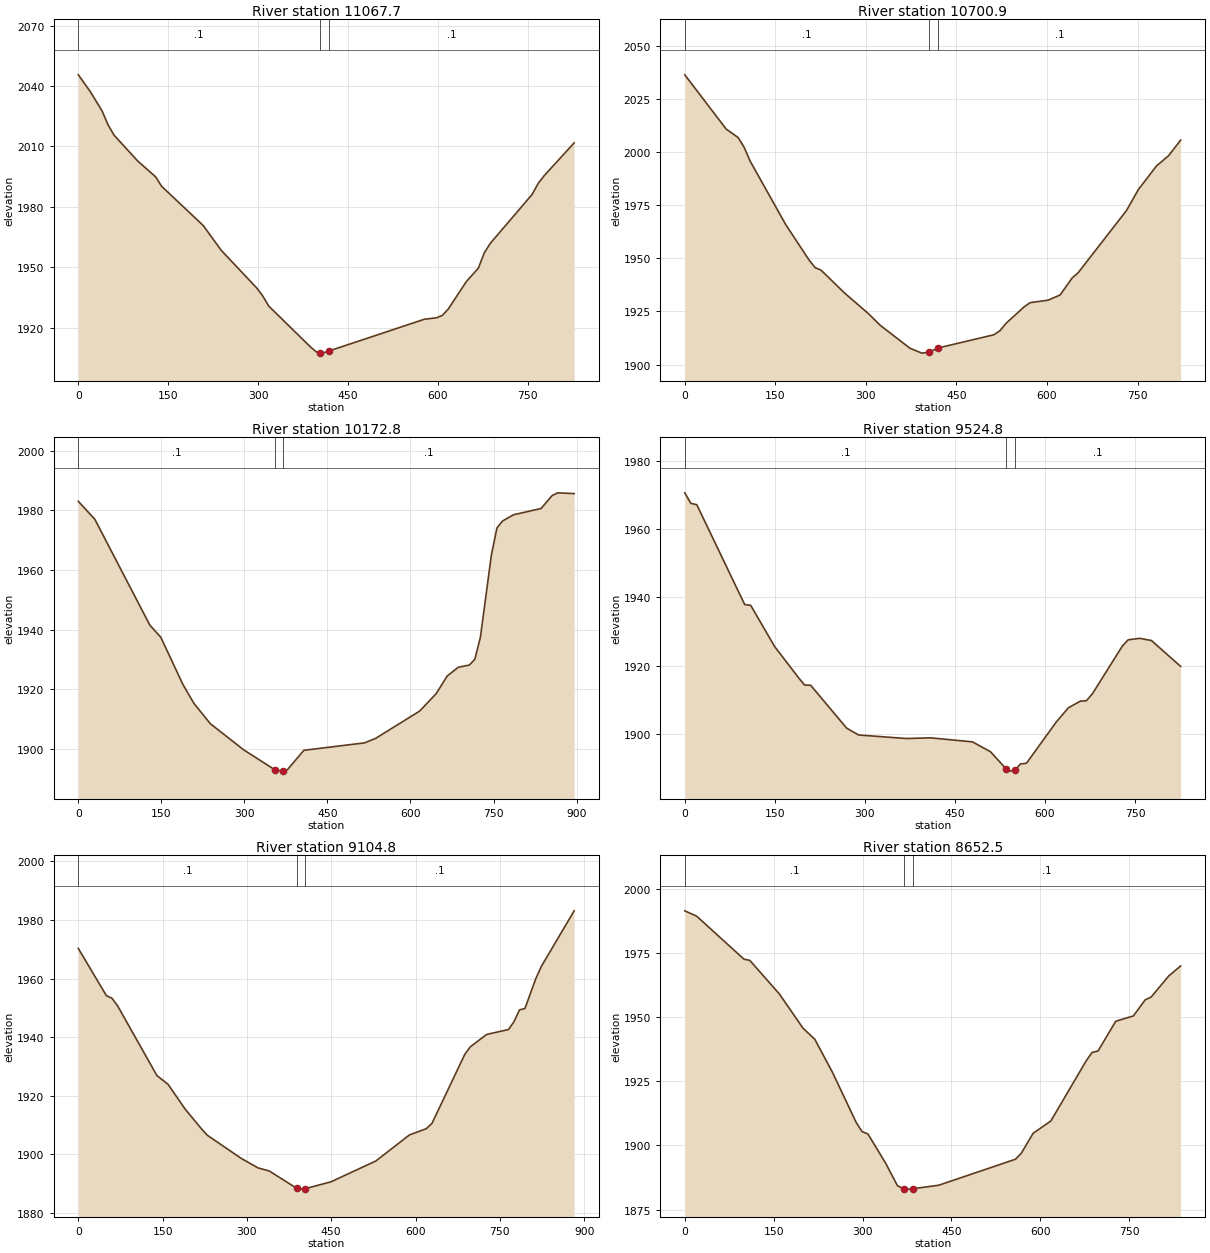
Type RM Length L Ch R = 1 ,11067.7,361.9,366.6,372.7
XS GIS Cut Line= 3
     1927049.465      318716.095     1927344.223      318804.715
     1927802.439      319049.905
#Sta/Elev= 30
       0 2045.56    19.9 2037.24    39.7 2027.59    49.6 2020.74    59.6 2015.60
    99.3 2002.69   129.1 1994.88   139.0 1990.19   208.5 1970.70   238.3 1958.45
   297.9 1939.63   307.8 1935.69   317.8 1930.69   387.7 1910.32   397.7 1907.83
   402.9 1907.56   407.7 1907.32   417.9 1908.35   577.6 1924.15   597.6 1924.86
   607.6 1926.06   617.6 1929.30   647.6 1942.88   667.6 1949.51   677.6 1957.19
   687.6 1961.86   757.5 1986.21   767.5 1991.64   777.5 1995.48   827.5 2011.77
#Mann= 3 , 0 , 0
       0     0.1       0   402.9   0.045       0   417.9     0.1       0
Bank Sta=   402.9,   417.9
Exp/Cntr=0.3,0.1

Type RM Length L Ch R = 1 ,10700.9,520.9,527.9,533.6
XS GIS Cut Line= 3
     1926946.507      318909.212     1927264.885      319171.089
     1927564.804      319449.195
#Sta/Elev= 30
       0 2036.28    68.7 2010.72    88.3 2006.79    98.2 2002.27   108.0 1995.82
   166.9 1965.96   206.1 1949.05   215.9 1945.59   225.8 1944.38   265.0 1933.53
   304.3 1923.92   323.9 1918.40   373.0 1907.66   392.6 1905.36   404.7 1905.79
   419.7 1907.79   512.0 1914.00   522.0 1915.91   532.0 1919.35   561.9 1927.08
   571.9 1929.10   601.8 1930.27   621.7 1932.72   641.7 1940.75   651.7 1943.22
   731.5 1972.39   751.4 1982.33   781.4 1993.44   801.3 1998.22   821.3 2005.54
#Mann= 3 , 0 , 0
       0     0.1       0   404.7   0.045       0   419.7     0.1       0
Bank Sta=   404.7,   419.7
Exp/Cntr=0.3,0.1

Type RM Length L Ch R = 1 ,10172.8,633.6,648,662.3
XS GIS Cut Line= 3
     1926684.496      319212.087     1926918.461      319569.545
     1927319.178      319812.287
#Sta/Elev= 30
       0 1983.05    29.8 1977.04   129.2 1941.50   149.0 1937.42   188.8 1921.63
   208.6 1915.29   238.4 1908.42   298.1 1899.71   354.7 1892.97   367.6 1892.48
   369.7 1892.57   377.5 1892.92   407.4 1899.47   516.9 1901.96   536.9 1903.46
   616.6 1912.64   646.5 1918.51   666.5 1924.44   686.4 1927.36   706.3 1928.09
   716.3 1930.05   726.3 1937.40   746.2 1965.10   756.2 1974.10   766.1 1976.43
   786.1 1978.55   835.9 1980.65   855.8 1984.98   865.8 1985.92   895.7 1985.66
#Mann= 3 , 0 , 0
       0     0.1       0   354.7   0.045       0   369.7     0.1       0
Bank Sta=   354.7,   369.7
Exp/Cntr=0.3,0.1

Type RM Length L Ch R = 1 ,9524.8,421.3,419.8,418.2
XS GIS Cut Line= 3
     1926521.646      319305.605     1926494.626      320033.837
     1926506.186      320130.163
#Sta/Elev= 30
       0 1970.56    10.0 1967.50    20.0 1967.08    99.8 1937.87   109.8 1937.64
   149.7 1925.57   189.7 1916.41   199.6 1914.32   209.6 1914.27   269.5 1901.73
   289.5 1899.71   369.4 1898.68   409.3 1898.88   479.2 1897.70   509.1 1894.82
   534.9 1889.87   539.1 1889.14   549.9 1889.33   559.0 1891.25   569.0 1891.43
   618.9 1903.56   638.9 1907.67   658.8 1909.61   668.8 1909.73   678.8 1911.74
   728.7 1925.72   738.4 1927.56   757.8 1927.99   777.2 1927.35   825.8 1919.78
#Mann= 3 , 0 , 0
       0     0.1       0   534.9   0.045       0   549.9     0.1       0
Bank Sta=   534.9,   549.9
Exp/Cntr=0.3,0.1

Type RM Length L Ch R = 1 ,9104.8,459.7,452.6,445.3
XS GIS Cut Line= 3
     1926155.919      319261.994     1926182.721      319890.598
     1926178.078      320143.631
#Sta/Elev= 30
       0 1970.26    49.9 1954.16    59.9 1953.25    69.9 1950.66   139.8 1926.87
   159.8 1923.83   189.8 1915.47   219.7 1908.53   229.7 1906.45   289.6 1898.60
   319.6 1895.33   339.6 1894.28   388.4 1888.37   399.5 1888.07   403.4 1888.21
   449.4 1890.56   529.3 1897.67   589.2 1906.59   619.2 1908.72   629.2 1910.53
   687.6 1934.09   697.3 1936.65   726.5 1940.90   765.4 1942.58   775.2 1945.28
   784.9 1949.28   794.6 1949.76   814.1 1960.03   823.8 1964.14   882.2 1983.12
#Mann= 3 , 0 , 0
       0     0.1       0   388.4   0.045       0   403.4     0.1       0
Bank Sta=   388.4,   403.4
Exp/Cntr=0.3,0.1

Type RM Length L Ch R = 1 ,8652.5,350.4,349,346.9
XS GIS Cut Line= 3
     1925681.299      319296.320     1925727.727      319500.603
     1925913.439      320099.524
#Sta/Elev= 30
       0 1991.38    20.0 1989.30    99.8 1972.56   109.7 1972.07   159.6 1958.99
   199.5 1945.67   219.4 1941.33   249.3 1928.41   289.1 1908.98   299.1 1905.38
   309.0 1904.46   338.9 1893.08   358.8 1884.30   370.2 1883.01   378.7 1882.97
   385.2 1883.13   428.5 1884.49   557.9 1894.61   567.8 1896.96   587.7 1904.71
   617.6 1909.50   677.3 1932.97   687.2 1936.21   697.2 1936.76   727.1 1948.36
   756.9 1950.44   776.8 1956.71   786.8 1957.78   816.6 1966.02   836.6 1969.90
#Mann= 3 , 0 , 0
       0     0.1       0   370.2   0.045       0   385.2     0.1       0
Bank Sta=   370.2,   385.2
Exp/Cntr=0.3,0.1

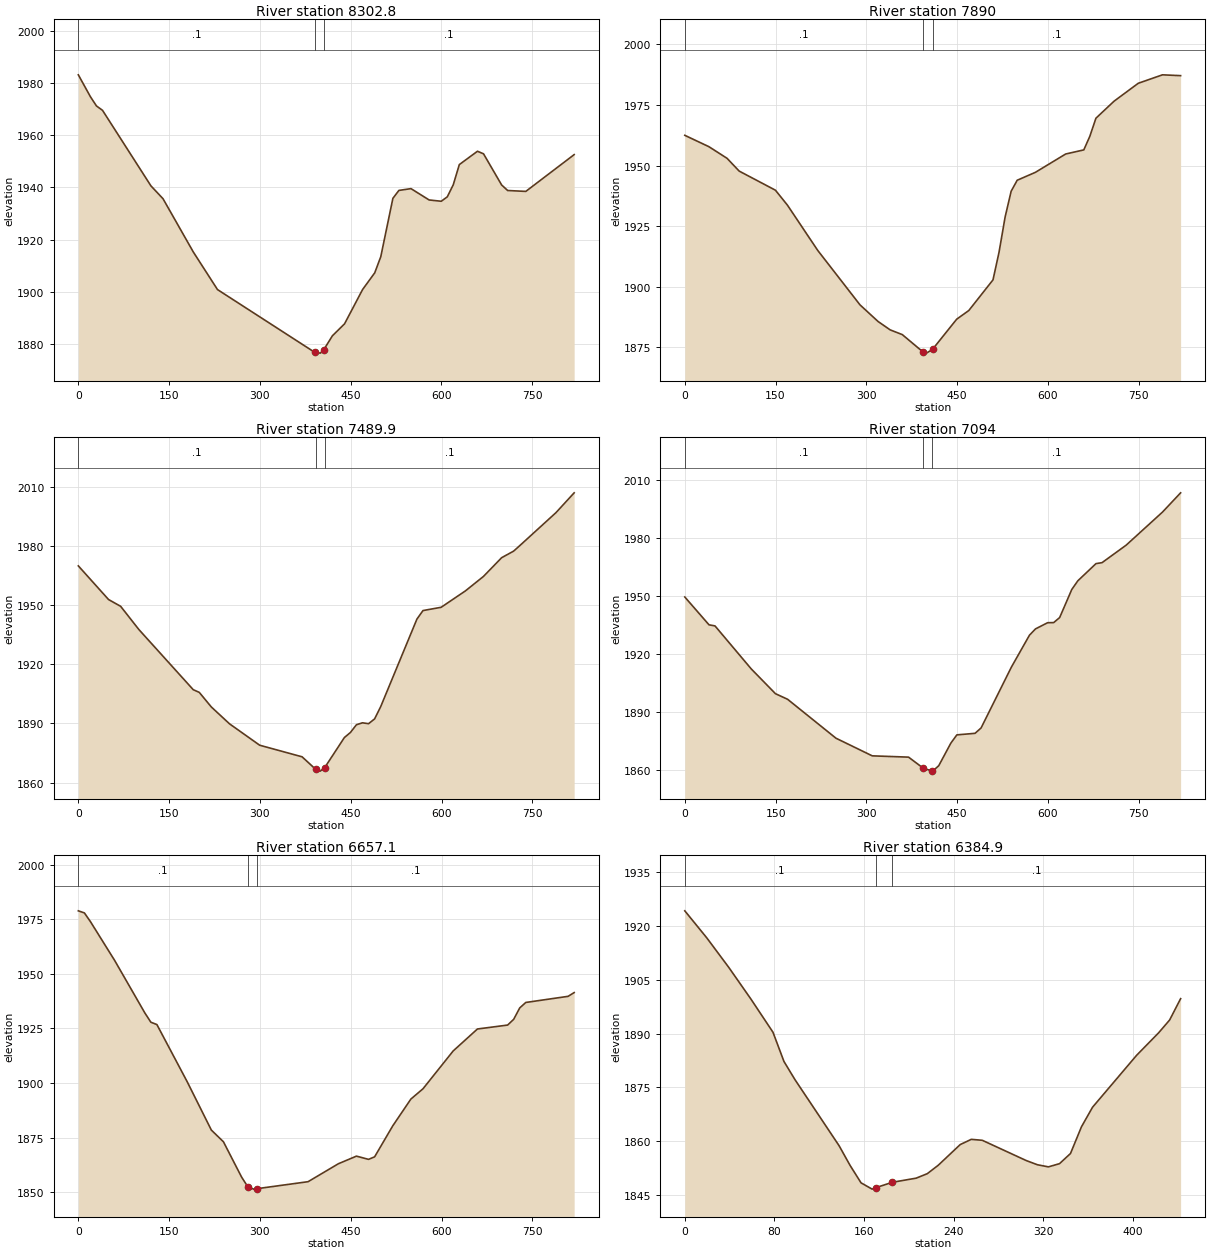
Type RM Length L Ch R = 1 ,8302.8,418.2,412.8,407.6
XS GIS Cut Line= 3
     1925346.146      319457.060     1925487.824      319841.810
     1925652.590      320216.667
#Sta/Elev= 30
       0 1983.12    20.0 1974.72    30.0 1971.19    40.0 1969.51   120.0 1940.58
   140.0 1935.64   190.0 1915.26   230.0 1900.85   390.6 1876.82   400.0 1876.50
   405.6 1877.78   420.0 1883.16   440.0 1887.72   469.9 1900.89   489.9 1907.26
   499.9 1913.45   519.9 1935.79   529.8 1938.83   549.8 1939.52   579.8 1935.18
   599.8 1934.68   609.8 1936.37   619.7 1941.01   629.7 1948.73   659.7 1953.84
   669.7 1952.86   699.6 1940.94   709.6 1938.80   739.6 1938.46   819.5 1952.55
#Mann= 3 , 0 , 0
       0     0.1       0   390.6   0.045       0   405.6     0.1       0
Bank Sta=   390.6,   405.6
Exp/Cntr=0.3,0.1

Type RM Length L Ch R = 1 ,7890,404.2,400,396.2
XS GIS Cut Line= 3
     1924900.029      319658.654     1925124.626      320000.929
     1925359.928      320336.874
#Sta/Elev= 30
       0 1962.48    39.9 1957.78    69.9 1952.97    89.9 1947.70   149.8 1939.81
   169.7 1933.61   219.7 1914.94   289.6 1892.43   319.5 1885.56   339.5 1882.10
   359.5 1880.15   394.4 1872.84   399.4 1872.50   409.4 1874.04   449.4 1886.52
   469.4 1890.10   509.4 1902.76   519.4 1914.21   529.4 1928.70   539.4 1939.38
   549.4 1943.92   579.4 1947.18   629.5 1954.76   659.5 1956.46   669.5 1962.11
   679.5 1969.54   709.5 1976.58   749.5 1983.98   789.5 1987.47   819.5 1987.13
#Mann= 3 , 0 , 0
       0     0.1       0   394.4   0.045       0   409.4     0.1       0
Bank Sta=   394.4,   409.4
Exp/Cntr=0.3,0.1

Type RM Length L Ch R = 1 ,7489.9,389.9,395.8,401.8
XS GIS Cut Line= 3
     1924561.145      319988.358     1924844.585      320283.911
     1925128.024      320579.465
#Sta/Elev= 30
       0 1970.03    49.9 1952.94    69.9 1949.49    99.9 1937.74   189.8 1907.15
   199.8 1905.78   219.7 1898.37   249.7 1889.82   299.6 1878.94   369.6 1873.06
   391.8 1866.78   399.5 1865.79   406.8 1867.50   439.5 1882.86   449.4 1885.40
   459.4 1889.36   469.4 1890.33   479.4 1889.88   489.4 1892.32   499.4 1898.51
   559.3 1943.01   569.3 1947.33   599.3 1949.00   639.2 1957.28   669.2 1964.67
   699.2 1974.18   719.1 1977.54   729.1 1980.29   789.0 1997.08   819.0 2007.13
#Mann= 3 , 0 , 0
       0     0.1       0   391.8   0.045       0   406.8     0.1       0
Bank Sta=   391.8,   406.8
Exp/Cntr=0.3,0.1

Type RM Length L Ch R = 1 ,7094,437.9,436.7,435.5
XS GIS Cut Line= 3
     1924336.086      320170.907     1924532.280      320530.348
     1924728.474      320889.790
#Sta/Elev= 30
       0 1949.33    40.0 1934.94    49.9 1934.38   109.9 1912.10   149.8 1899.33
   169.8 1896.45   249.7 1876.33   309.6 1867.21   369.6 1866.54   393.7 1860.88
   408.7 1859.33   409.5 1859.31   419.5 1862.13   439.5 1873.80   449.4 1878.05
   479.4 1878.85   489.4 1881.62   539.3 1912.98   569.3 1929.57   579.3 1932.84
   599.3 1936.03   609.3 1936.10   619.2 1938.70   639.2 1953.20   649.2 1957.69
   679.2 1966.58   689.2 1967.08   729.1 1976.14   789.0 1993.21   819.0 2003.18
#Mann= 3 , 0 , 0
       0     0.1       0   393.7   0.045       0   408.7     0.1       0
Bank Sta=   393.7,   408.7
Exp/Cntr=0.3,0.1

Type RM Length L Ch R = 1 ,6657.1,284.7,271.8,259
XS GIS Cut Line= 3
     1923972.017      320385.469     1924187.861      320733.466
     1924403.704      321081.463
#Sta/Elev= 30
       0 1978.84    10.0 1977.88    20.0 1973.90    59.9 1956.18   109.9 1932.10
   119.8 1927.87   129.8 1926.78   179.8 1900.63   219.7 1878.51   239.7 1873.14
   269.7 1856.98   279.9 1852.57   289.6 1851.48   294.9 1851.68   379.5 1854.88
   429.5 1863.09   459.4 1866.58   479.4 1865.10   489.4 1866.26   519.4 1880.45
   549.3 1892.69   569.3 1897.40   619.2 1914.72   659.2 1924.76   709.1 1926.56
   719.1 1929.18   729.1 1934.40   739.1 1936.90   809.0 1939.71   819.0 1941.42
#Mann= 3 , 0 , 0
       0     0.1       0   279.9   0.045       0   294.9     0.1       0
Bank Sta=   279.9,   294.9
Exp/Cntr=0.3,0.1

Type RM Length L Ch R = 1 ,6384.9,260.1,269.5,278.8
XS GIS Cut Line= 2
     1923837.762      320767.524     1924234.699      320963.158
#Sta/Elev= 30
       0 1924.26    19.7 1916.69    39.3 1908.46    59.0 1899.65    78.7 1890.39
    88.5 1882.24    98.3 1877.18   137.7 1858.74   147.5 1853.25   157.3 1848.38
   167.2 1846.63   170.3 1847.02   185.3 1848.54   206.5 1849.69   216.4 1850.94
   226.2 1853.29   245.8 1859.06   255.7 1860.52   265.5 1860.25   304.8 1854.59
   314.7 1853.43   324.5 1852.84   334.4 1853.73   344.2 1856.56   354.0 1864.01
   363.9 1869.48   403.2 1883.95   422.9 1890.24   432.7 1893.81   442.5 1899.76
#Mann= 3 , 0 , 0
       0     0.1       0   170.3   0.045       0   185.3     0.1       0
Bank Sta=   170.3,   185.3
Exp/Cntr=0.3,0.1