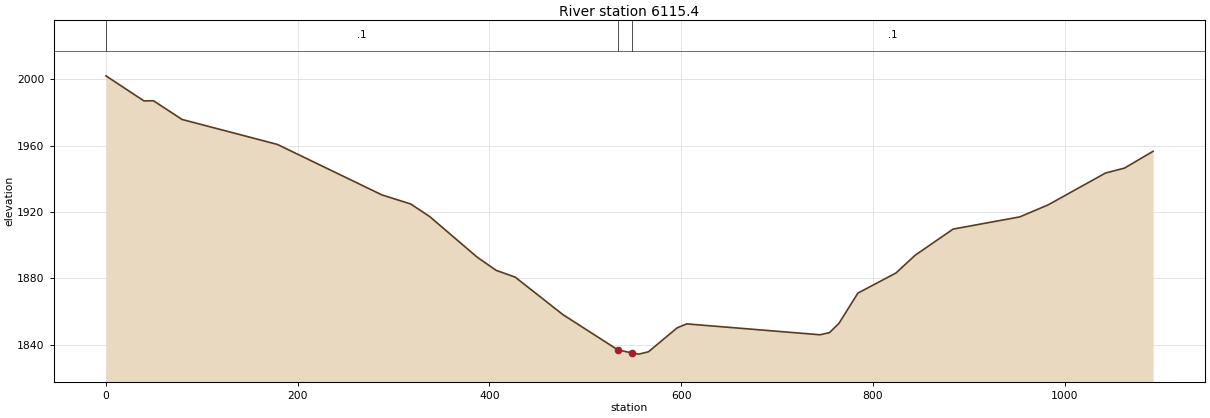
HEC-RAS study MllCrk.prj: MllCrk

--- MllCrk.g01 (geometry) --- (continued)

Type RM Length L Ch R = 1 ,6115.4,6122.5,6113.6,6102.9
XS GIS Cut Line= 2
     1923447.403      320627.426     1924173.988      321442.618
#Sta/Elev= 30
       0 2002.05    39.7 1986.93    49.6 1987.03    79.4 1975.75   178.7 1960.72
   287.9 1930.25   317.7 1924.83   337.5 1917.29   387.2 1892.72   407.0 1884.79
   426.9 1880.67   476.5 1858.14   533.7 1836.90   548.7 1834.96   555.9 1834.28
   565.8 1835.70   595.6 1850.07   605.6 1852.51   744.6 1845.96   754.5 1847.21
   764.4 1852.80   784.2 1871.06   824.0 1883.23   843.8 1893.84   883.5 1909.66
   953.0 1917.01   982.8 1924.31  1042.4 1943.44  1062.2 1946.43  1092.0 1956.54
#Mann= 3 , 0 , 0
       0     0.1       0   533.7   0.045       0   548.7     0.1       0
Bank Sta=   533.7,   548.7
Exp/Cntr=0.3,0.1